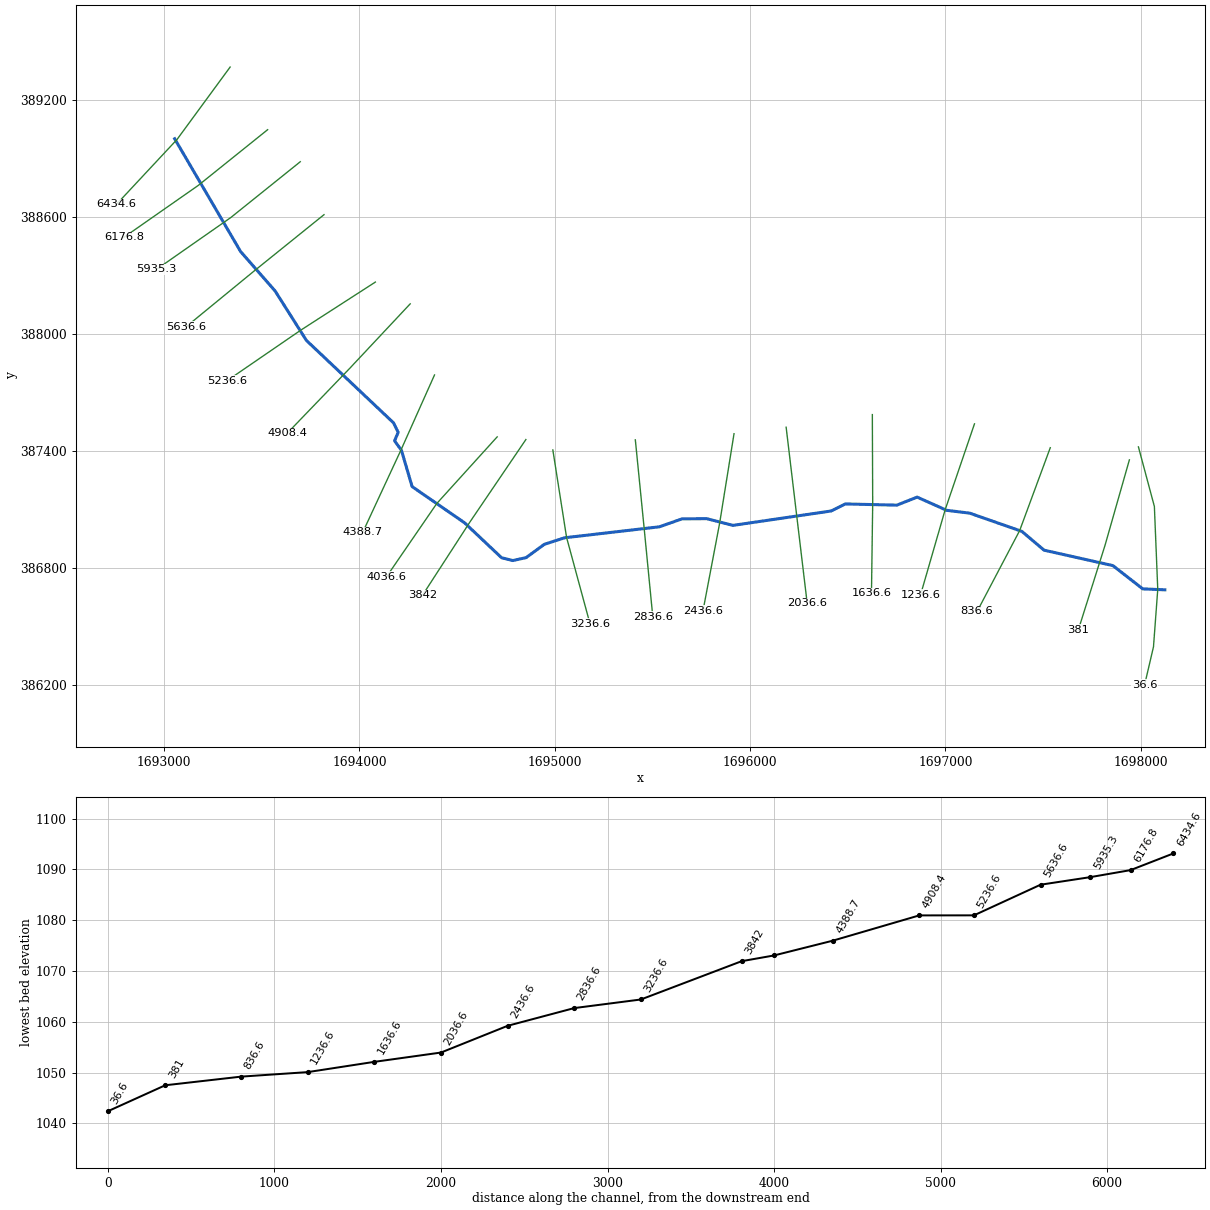
--- StrkyRn.prj (project) ---

Proj Title=StrkyRn
Current Plan=p01
Geom File=g01
Flow File=f01
Plan File=p01
DSS Export Rating Curves=0
DSS Export Rating Curve Sorted=0
DSS Export Volume Flow Curves=0
DXF OffsetX=0
DXF OffsetY=0
DXF ScaleX=0
DXF ScaleY=0

--- StrkyRn.p01 (plan) ---

Plan Title=Floodplain
Program Version=4.00
Geom File=g01
Flow File=f01
K Sum by GR=0
Std Step Tol=0.01
Critical Tol=0.01
Num of Std Step Trials=20
Max Error Tol=0.3
Flow Tol Ratio=0.001
Split Flow NTrial=30
Split Flow Tol=0.02
Split Flow Ratio=0.02
Log Output Level=0
Friction Slope Method=1
Unsteady Friction Slope Method=2
Unsteady Bridges Friction Slope Method=1
Global Log Level=0
CheckData=False
Run HTab=0
Run UNet=0
Run PostProcess=0
UNET Theta=0
UNET Theta Warmup=0
UNET ZTol=0
UNET ZSATol=0
UNET MxIter=0
UNET MaxInSteps=0
UNET DtIC=0
UNET DtMin=0
UNET MaxCRTS=0
UNET WFStab=0
UNET SFStab=0
UNET WFX=0
UNET SFX=0
UNET DSS MLevel=0
UNET DZMax Abort=0
UNET Convert EG Bridges=0
UNET Use Existing IB Tables=0
UNET Froude Limit=0
UNET Froude Power=0
Write IC File=0
Echo Input=False
Echo Output=False
Write Detailed=0

--- StrkyRn.f01 (steady flow) ---

Flow Title=NFF Regression Equation
Program Version=4.00
Number of Profiles=1
Profile Names=P100yr
River Rch & RM=StrkyRn,Main      ,6434.6
558.9948
River Rch & RM=StrkyRn,Main      ,6176.8
558.9948
River Rch & RM=StrkyRn,Main      ,5935.3
734.7888
River Rch & RM=StrkyRn,Main      ,4388.7
755.7722
River Rch & RM=StrkyRn,Main      ,4036.6
843.7612
River Rch & RM=StrkyRn,Main      ,3236.6
870.4608
River Rch & RM=StrkyRn,Main      ,381
961.5882
River Rch & RM=StrkyRn,Main      ,36.6
961.5882
Boundary for River Rch & Prof#=StrkyRn,Main      ,1
Up Type=0
Dn Type=3
Dn Slope=0.006436

--- StrkyRn.g01 (geometry) ---

Geom Title=USGS 3m DEM
Program Version=4.00

River Reach=StrkyRn     ,Main
Reach XY= 30
     1693053.965      388999.088     1693391.341      388421.240
     1693568.184      388219.031     1693728.870      387965.033
     1694174.127      387543.386     1694198.317      387494.456
     1694179.882      387450.690     1694215.044      387402.252
     1694269.749      387216.210     1694538.156      387030.786
     1694727.651      386851.653     1694785.256      386837.230
     1694853.246      386852.188     1694946.675      386920.486
     1695050.978      386953.983     1695535.741      387010.245
     1695651.748      387050.945     1695777.866      387051.908
     1695912.443      387017.485     1696414.927      387091.220
     1696487.680      387127.321     1696751.316      387121.193
     1696855.365      387162.272     1697006.651      387094.701
     1697124.567      387080.126     1697391.429      386986.772
     1697505.115      386890.418     1697857.592      386811.297
     1698010.268      386692.058     1698123.517      386687.246

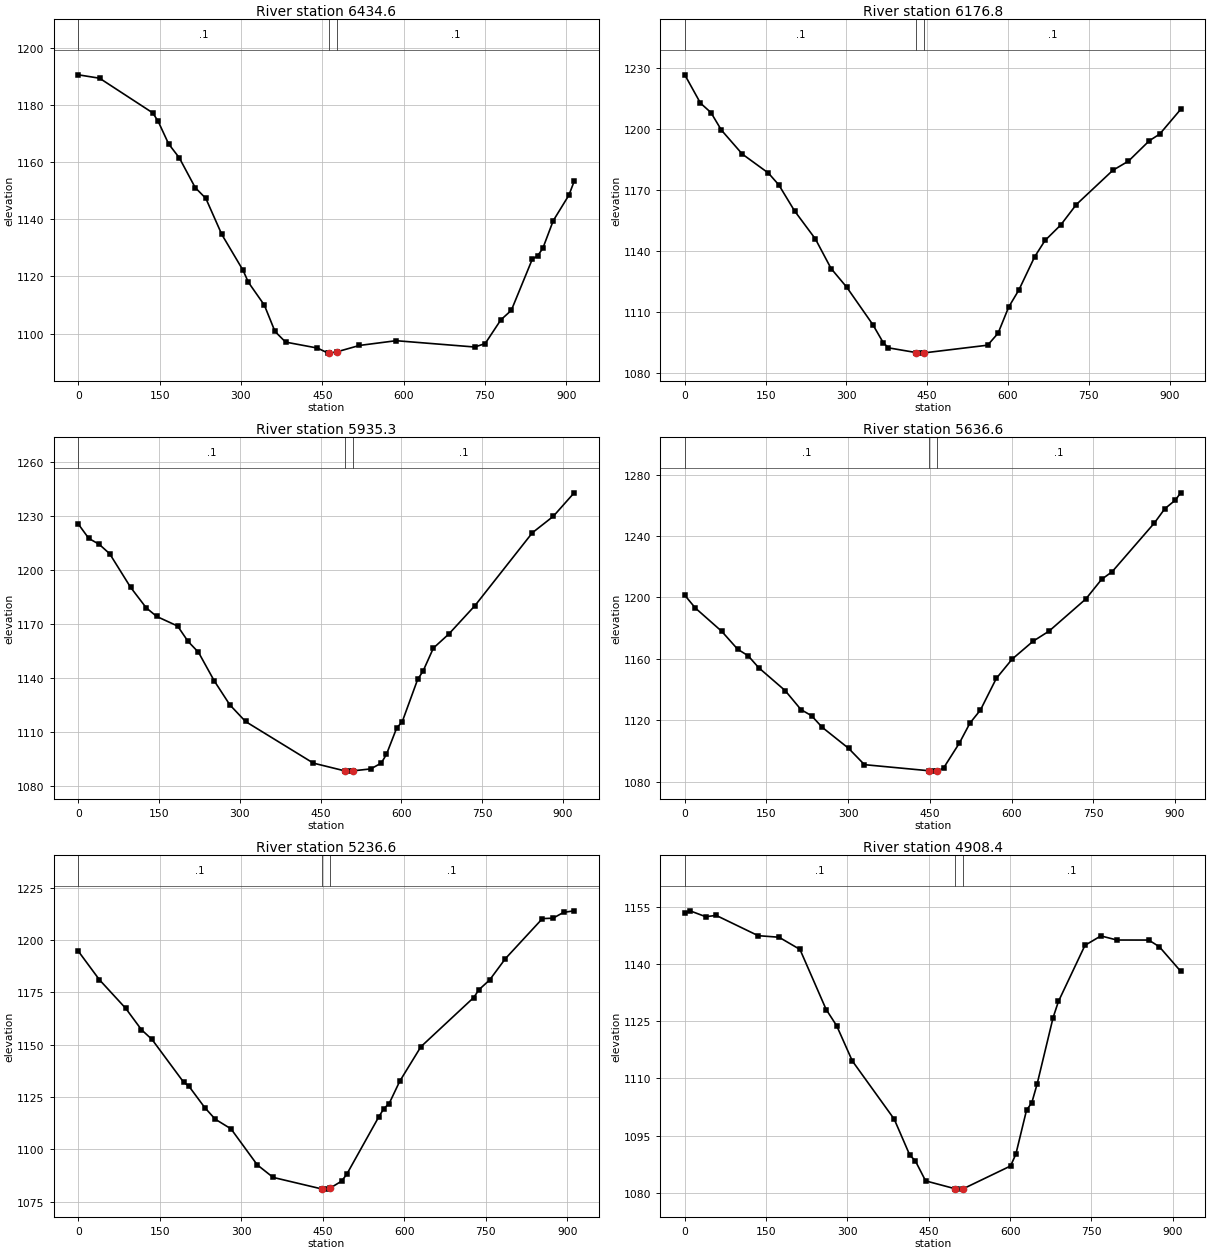
Type RM Length L Ch R = 1 ,6434.6,263.986,257.78,253.294
XS GIS Cut Line= 3
     1693338.062      389366.632     1693065.735      388995.066
     1692756.136      388663.069
#Sta/Elev= 30
       0 1190.54    39.2 1189.35   137.2 1177.23   147.0 1174.36   166.6 1166.35
   186.2 1161.51   215.6 1151.07   235.2 1147.30   264.6 1134.69   303.9 1122.11
   313.7 1117.93   343.1 1109.96   362.7 1100.75   382.3 1097.01   441.1 1094.92
   460.7 1093.15   462.4 1093.18   477.4 1093.63   518.6 1095.84   586.2 1097.50
   731.1 1095.29   750.4 1096.48   779.4 1104.80   798.7 1108.13   837.4 1126.04
   847.0 1127.16   856.7 1129.78   876.0 1139.49   905.0 1148.46   914.6 1153.28
#Mann= 3 , 0 , 0
       0     0.1       0   462.4   0.045       0   477.4     0.1       0
Bank Sta=   462.4,   477.4
Exp/Cntr=0.3,0.1

Type RM Length L Ch R = 1 ,6176.8,242.587,241.489,240.816
XS GIS Cut Line= 3
     1693529.851      389045.426     1693174.617      388759.787
     1692793.715      388493.513
#Sta/Elev= 30
       0 1226.54    29.1 1212.63    48.5 1208.02    67.9 1199.41   106.7 1187.63
   155.2 1178.30   174.6 1172.46   203.7 1159.75   242.5 1145.92   271.6 1131.41
   300.7 1122.22   349.1 1103.87   368.5 1094.97   378.2 1092.45     429 1090.16
   436.4 1089.86     444 1089.97   562.3 1093.76   581.7 1099.65   601.1 1112.35
   620.4 1120.94   649.5 1137.14   668.8 1145.18   697.9 1152.77   726.9 1162.82
   794.7 1179.64   823.8 1184.17   862.5 1194.18   881.8 1197.45   920.6 1209.55
#Mann= 3 , 0 , 0
       0     0.1       0     429   0.045       0     444     0.1       0
Bank Sta=     429,     444
Exp/Cntr=0.3,0.1

Type RM Length L Ch R = 1 ,5935.3,296.449,298.664,300.303
XS GIS Cut Line= 3
     1693697.121      388881.313     1693341.887      388595.673
     1692960.984      388329.400
#Sta/Elev= 30
       0 1225.76    19.4 1217.80    38.8 1214.50    58.2 1209.28    97.0 1190.63
   126.1 1179.22   145.5 1174.43   184.3 1169.11   203.7 1160.57   223.1 1154.50
   252.2 1138.72   281.3 1125.31   310.4 1116.07   436.4 1092.92   494.5 1088.64
   504.2 1088.48   509.5 1088.62   543.0 1089.72   562.3 1092.92   572.0 1097.73
   591.4 1112.69   601.1 1115.69   630.1 1139.52   639.8 1143.89   659.2 1156.84
   688.2 1164.76   736.6 1180.51   843.1 1220.97   881.8 1230.06   920.6 1243.13
#Mann= 3 , 0 , 0
       0     0.1       0   494.5   0.045       0   509.5     0.1       0
Bank Sta=   494.5,   509.5
Exp/Cntr=0.3,0.1

Type RM Length L Ch R = 1 ,5636.6,398.367,400,396.427
XS GIS Cut Line= 3
     1693818.518      388609.895     1693463.661      388323.560
     1693112.192      388035.117
#Sta/Elev= 30
       0 1201.41    19.4 1193.11    67.9 1177.93    97.0 1166.34   116.4 1162.03
   135.8 1154.26   184.3 1139.40   213.4 1127.01   232.8 1123.04   252.2 1115.55
   300.7 1101.86   329.9 1091.20   448.5 1087.23   456.0 1086.99   463.5 1087.03
   475.3 1089.05   504.3 1105.25   523.7 1118.26   543.0 1126.77   572.1 1147.32
   601.1 1159.84   639.8 1171.56   668.8 1178.05   736.5 1199.01   765.5 1211.78
   784.9 1216.77   862.3 1248.40   881.6 1257.75   901.0 1263.35   910.6 1268.08
#Mann= 3 , 0 , 0
       0     0.1       0   448.5   0.045       0   463.5     0.1       0
Bank Sta=   448.5,   463.5
Exp/Cntr=0.3,0.1

Type RM Length L Ch R = 1 ,5236.6,322.453,328.273,333.17
XS GIS Cut Line= 3
     1694081.609      388264.568     1693699.115      388017.693
     1693322.387      387758.976
#Sta/Elev= 30
       0 1194.61    38.7 1181.00    87.2 1167.31   116.2 1157.09   135.6 1152.45
   193.7 1132.05   203.4 1130.14   232.5 1119.95   251.8 1114.39   280.9 1109.75
   329.3 1092.53   358.4 1086.56   447.7 1081.06   455.2 1080.96   462.7 1081.35
   484.4 1084.78   494.1 1088.16   552.5 1115.34   562.2 1119.43   571.9 1121.85
   591.4 1132.50   630.3 1148.98   727.5 1172.49   737.2 1176.24   756.7 1180.85
   785.8 1191.06   853.9 1210.19   873.4 1210.38   892.8 1213.16   912.3 1213.90
#Mann= 3 , 0 , 0
       0     0.1       0   447.7   0.045       0   462.7     0.1       0
Bank Sta=   447.7,   462.7
Exp/Cntr=0.3,0.1

Type RM Length L Ch R = 1 ,4908.4,508.74,519.705,533.863
XS GIS Cut Line= 3
     1694259.795      388152.872     1693949.612      387821.693
     1693630.230      387489.741
#Sta/Elev= 30
       0 1153.29     9.7 1153.88    38.6 1152.34    57.9 1152.68   135.2 1147.37
   173.8 1146.96   212.4 1143.76   260.7 1128.02   280.0 1123.79   308.9 1114.55
   386.2 1099.29   415.1 1089.80   424.8 1088.45   444.1 1083.11   498.8 1081.04
   502.8 1080.95   513.8 1081.07   600.8 1087.02   610.6 1090.15   630.2 1101.64
   640.0 1103.62   649.8 1108.52   679.2 1125.89   689.0 1130.12   738.0 1144.84
   767.4 1147.31   796.8 1146.23   855.6 1146.22   875.2 1144.46   914.4 1138.06
#Mann= 3 , 0 , 0
       0     0.1       0   498.8   0.045       0   513.8     0.1       0
Bank Sta=   498.8,   513.8
Exp/Cntr=0.3,0.1

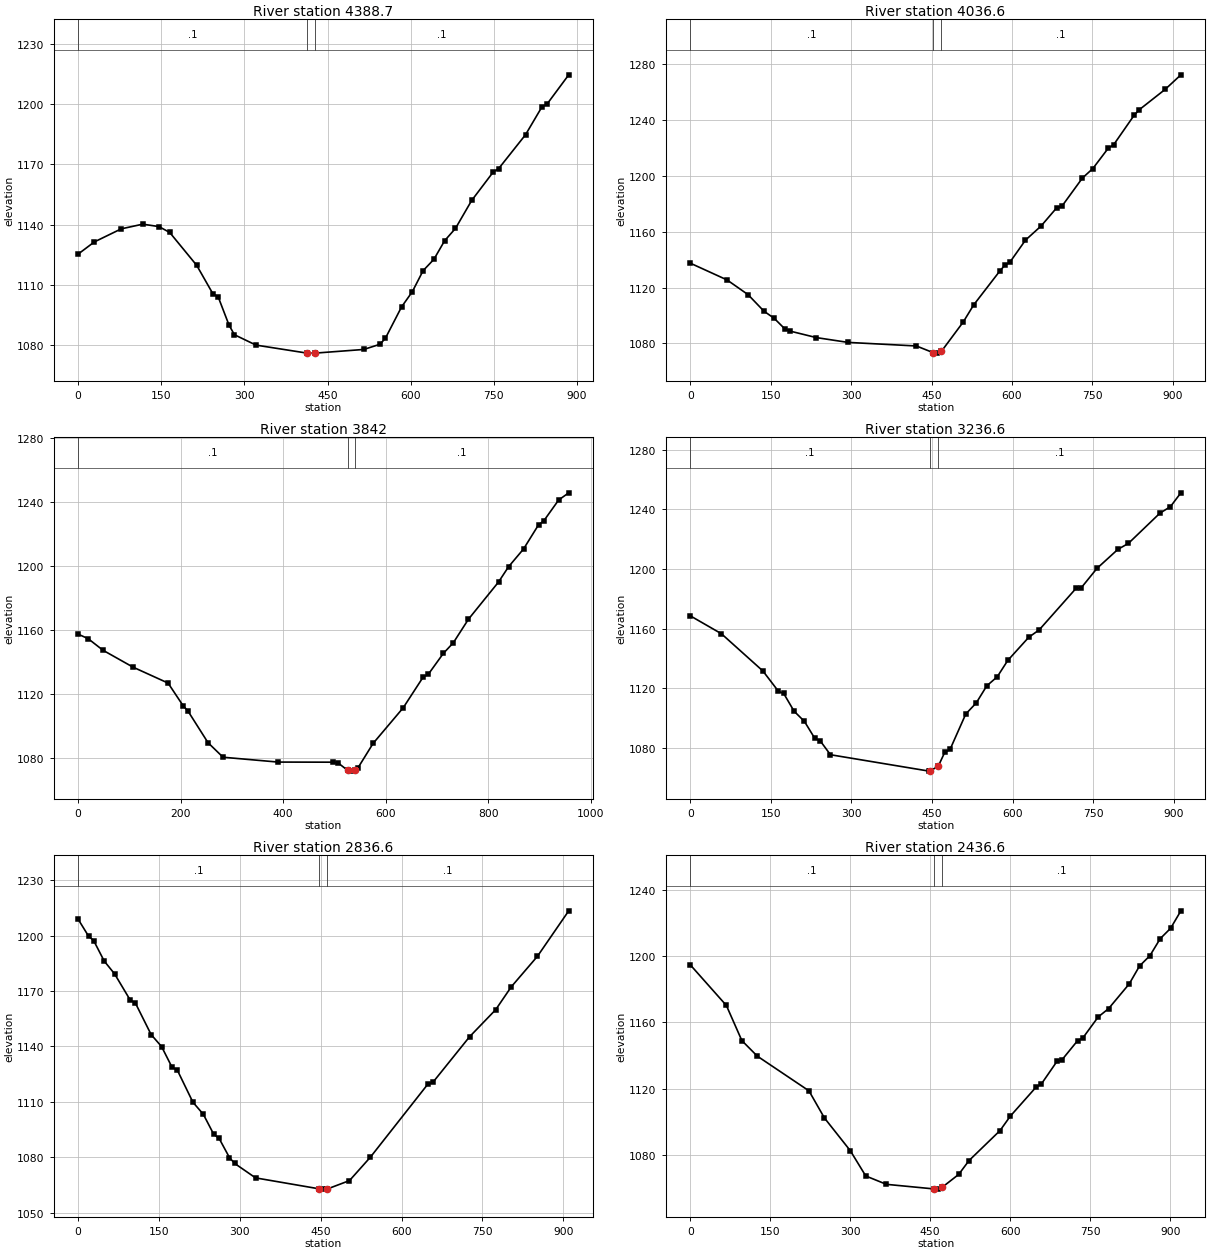
Type RM Length L Ch R = 1 ,4388.7,360.959,352.022,342.941
XS GIS Cut Line= 3
     1694384.376      387788.555     1694213.951      387406.676
     1694017.483      386983.148
#Sta/Elev= 30
       0 1125.27    29.2 1131.34    77.8 1137.87   116.7 1140.21   145.9 1139.00
   165.3 1136.08   214.0 1119.69   243.1 1105.58   252.9 1103.88   272.3 1089.93
   282.0 1085.14   320.9 1079.97   412.3 1076.01   427.3 1075.97   515.4 1077.80
   544.6 1080.38   554.4 1083.38   583.5 1098.97   603.0 1106.60   622.4 1117.05
   641.9 1122.71   661.3 1131.99   680.8 1138.10   710.0 1152.01   748.9 1166.19
   758.6 1167.86   807.2 1184.77   836.4 1198.46   846.2 1200.11   885.1 1214.60
#Mann= 3 , 0 , 0
       0     0.1       0   412.3   0.045       0   427.3     0.1       0
Bank Sta=   412.3,   427.3
Exp/Cntr=0.3,0.1

Type RM Length L Ch R = 1 ,4036.6,190.886,194.589,195.243
XS GIS Cut Line= 3
     1694705.188      387471.203     1694395.838      387129.391
     1694139.191      386754.968
#Sta/Elev= 30
       0 1137.47    68.7 1125.45   107.9 1114.91   137.3 1103.16   156.9 1097.87
   176.6 1090.34   186.4 1088.81   235.4 1084.17   294.3 1080.75   421.8 1078.19
   453.5 1073.34   461.0 1073.07   468.5 1074.38   509.3 1095.45   528.6 1107.58
   576.9 1131.61   586.6 1135.95   596.2 1138.17   625.2 1153.94   654.2 1164.01
   683.2 1176.99   692.8 1178.02   731.4 1198.39   750.8 1205.16   779.7 1219.80
   789.4 1222.08   828.0 1243.39   837.7 1247.35   886.0 1261.93   915.0 1272.24
#Mann= 3 , 0 , 0
       0     0.1       0   453.5   0.045       0   468.5     0.1       0
Bank Sta=   453.5,   468.5
Exp/Cntr=0.3,0.1

Type RM Length L Ch R = 1 ,3842,588.88,605.411,624.403
XS GIS Cut Line= 3
     1694852.162      387457.408     1694567.729      387037.876
     1694323.304      386660.121
#Sta/Elev= 30
       0 1157.60    19.5 1154.79    48.7 1147.50   107.2 1136.95   175.5 1127.00
   204.7 1112.91   214.4 1109.45   253.4 1089.72   282.7 1080.63   389.9 1077.60
   497.1 1077.53   506.9 1077.10   525.7 1072.43   536.2 1071.94   540.7 1072.92
   546.0 1074.08   575.3 1089.27   634.0 1111.54   673.1 1130.83   682.9 1132.46
   712.3 1145.55   731.8 1152.22   761.2 1166.91   819.9 1190.18   839.4 1199.71
   868.8 1210.89   898.1 1226.04   907.9 1228.31   937.2 1241.48   956.8 1245.95
#Mann= 3 , 0 , 0
       0     0.1       0   525.7   0.045       0   540.7     0.1       0
Bank Sta=   525.7,   540.7
Exp/Cntr=0.3,0.1

Type RM Length L Ch R = 1 ,3236.6,401.268,400,396.225
XS GIS Cut Line= 3
     1694990.156      387404.290     1695060.581      386955.490
     1695180.606      386512.448
#Sta/Elev= 30
       0 1168.53    58.0 1156.51   135.3 1131.52   164.3 1117.87   174.0 1116.45
   193.3 1104.59   212.6 1097.71   232.0 1086.28   241.6 1084.88   261.0 1075.39
   444.6 1064.40   446.8 1064.52   461.8 1067.79   473.8 1077.04   483.6 1078.92
   512.9 1102.69   532.4 1110.12   552.0 1121.57   571.5 1127.65   591.0 1138.57
   630.1 1154.12   649.6 1159.10   718.0 1186.86   727.7 1187.25   757.0 1200.26
   796.1 1213.08   815.6 1217.06   874.2 1237.30   893.8 1241.68   913.3 1250.96
#Mann= 3 , 0 , 0
       0     0.1       0   446.8   0.045       0   461.8     0.1       0
Bank Sta=   446.8,   461.8
Exp/Cntr=0.3,0.1

Type RM Length L Ch R = 1 ,2836.6,405.905,400,393.459
XS GIS Cut Line= 3
     1695412.551      387455.720     1695457.650      387002.959
     1695501.823      386550.109
#Sta/Elev= 30
       0 1209.00    19.4 1199.78    29.0 1197.33    48.4 1186.31    67.8 1179.29
    96.8 1165.09   106.5 1163.41   135.5 1146.44   154.9 1139.93   174.3 1128.71
   183.9 1127.28   213.0 1109.78   232.3 1103.26   251.7 1092.36   261.4 1090.29
   280.7 1079.84   290.4 1076.63   329.2 1068.80   447.5 1062.85   455.0 1062.71
   462.5 1062.82   503.4 1067.34   542.1 1080.01   648.6 1119.55   658.3 1120.65
   726.1 1145.27   774.5 1159.92   803.5 1172.35   851.9 1188.83   910.0 1213.49
#Mann= 3 , 0 , 0
       0     0.1       0   447.5   0.045       0   462.5     0.1       0
Bank Sta=   447.5,   462.5
Exp/Cntr=0.3,0.1

Type RM Length L Ch R = 1 ,2436.6,393.773,400,406.91
XS GIS Cut Line= 3
     1695917.811      387487.243     1695844.102      387028.510
     1695759.248      386581.072
#Sta/Elev= 30
       0 1194.90    67.8 1170.27    96.8 1149.05   125.8 1139.64   222.6 1118.67
   251.7 1102.22   300.1 1082.49   329.1 1067.18   367.8 1062.12   457.1 1059.34
   464.6 1059.22   472.1 1060.25   503.4 1068.13   522.8 1076.51   580.9 1094.63
   600.3 1103.40   648.7 1120.98   658.4 1122.79   687.5 1136.41   697.2 1137.48
   726.2 1148.95   735.9 1150.52   765.0 1163.36   784.4 1168.37   823.1 1183.31
   842.5 1194.17   861.9 1200.38   881.3 1210.71   900.7 1216.94   920.0 1227.52
#Mann= 3 , 0 , 0
       0     0.1       0   457.1   0.045       0   472.1     0.1       0
Bank Sta=   457.1,   472.1
Exp/Cntr=0.3,0.1

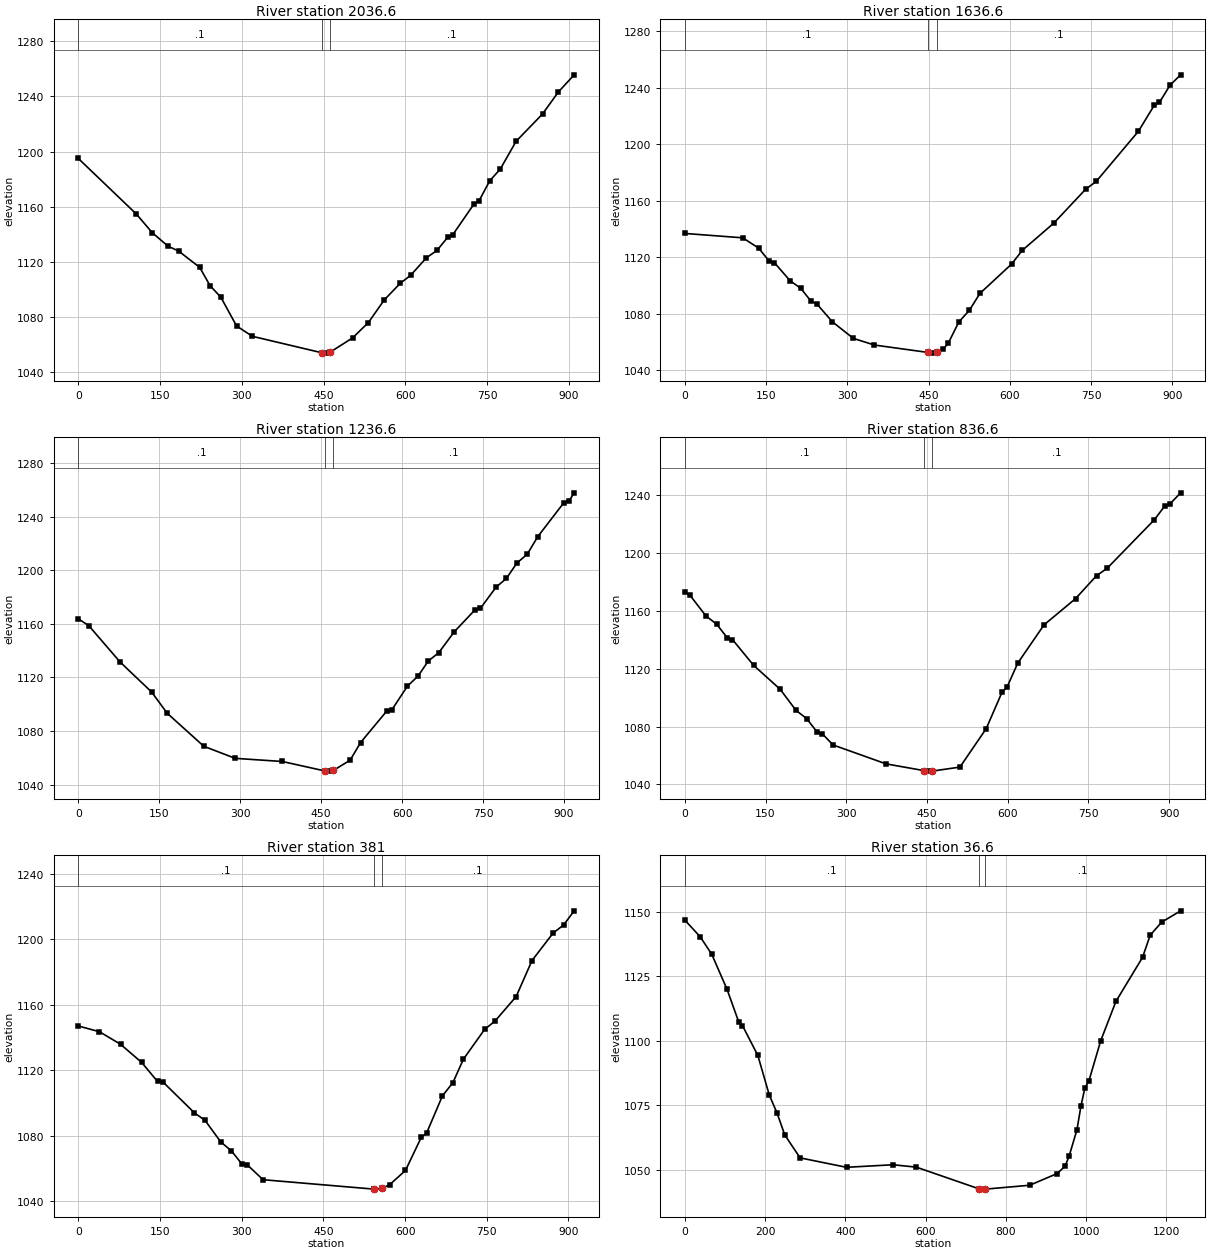
Type RM Length L Ch R = 1 ,2036.6,402.667,400,396.94
XS GIS Cut Line= 3
     1696184.604      387520.691     1696238.544      387068.899
     1696292.485      386617.108
#Sta/Elev= 30
       0 1194.95   106.5 1154.70   135.5 1141.27   164.6 1131.41   183.9 1127.94
   222.7 1116.09   242.0 1102.68   261.4 1094.57   290.4 1073.65   319.5 1066.13
   447.5 1054.17   455.0 1053.96   462.5 1054.75   503.4 1065.01   532.4 1076.12
   561.5 1092.52   590.5 1104.41   609.9 1110.33   638.9 1123.06   658.3 1128.37
   677.7 1137.77   687.3 1139.76   726.1 1161.97   735.7 1164.47   755.1 1178.81
   774.5 1187.32   803.5 1207.43   851.9 1227.15   881.0 1243.12   910.0 1255.55
#Mann= 3 , 0 , 0
       0     0.1       0   447.5   0.045       0   462.5     0.1       0
Bank Sta=   447.5,   462.5
Exp/Cntr=0.3,0.1

Type RM Length L Ch R = 1 ,1636.6,407.59,400,393.873
XS GIS Cut Line= 3
     1696625.962      387585.292     1696627.777      387128.211
     1696621.483      386670.101
#Sta/Elev= 30
       0 1136.92   107.0 1133.81   136.2 1126.55   155.6 1117.41   165.3 1116.25
   194.5 1103.35   214.0 1098.05   233.4 1088.73   243.1 1087.25   272.3 1074.35
   311.2 1062.55   350.1 1057.86   449.6 1052.58   457.1 1052.13   464.6 1053.19
   476.6 1054.77   486.3 1059.16   505.8 1074.17   525.3 1082.51   544.8 1094.45
   603.3 1115.27   622.8 1124.88   681.3 1144.30   739.8 1168.21   759.3 1173.73
   837.3 1209.31   866.5 1227.69   876.2 1229.79   895.7 1241.99   915.2 1249.29
#Mann= 3 , 0 , 0
       0     0.1       0   449.6   0.045       0   464.6     0.1       0
Bank Sta=   449.6,   464.6
Exp/Cntr=0.3,0.1

Type RM Length L Ch R = 1 ,1236.6,400.585,400,395.395
XS GIS Cut Line= 3
     1697148.852      387537.831     1696998.763      387097.626
     1696872.887      386661.809
#Sta/Elev= 30
       0 1163.71    19.4 1158.59    77.5 1131.43   135.7 1109.15   164.7 1093.27
   232.5 1068.64   290.7 1059.64   377.9 1057.30   457.6 1050.17   465.1 1050.11
   472.6 1050.62   503.7 1058.32   523.0 1071.43   571.3 1094.84   580.9 1095.81
   609.9 1113.57   629.2 1120.88   648.5 1132.27   667.8 1138.45   696.7 1154.10
   735.3 1170.55   745.0 1171.49   773.9 1187.28   793.2 1193.86   812.6 1205.31
   831.9 1211.97   851.2 1224.97   899.4 1250.20   909.1 1251.59   918.7 1257.68
#Mann= 3 , 0 , 0
       0     0.1       0   457.6   0.045       0   472.6     0.1       0
Bank Sta=   457.6,   472.6
Exp/Cntr=0.3,0.1

Type RM Length L Ch R = 1 ,836.6,454.505,455.673,459.792
XS GIS Cut Line= 3
     1697536.935      387415.508     1697380.237      386990.902
     1697162.206      386576.099
#Sta/Elev= 30
       0 1173.03     9.8 1170.53    39.4 1156.28    59.0 1150.71    78.7 1141.36
    88.6 1140.00   127.9 1122.23   177.1 1105.75   206.6 1091.15   226.3 1085.52
   246.0 1076.11   255.8 1074.86   275.5 1067.28   373.9 1054.23   445.1 1049.52
   452.6 1049.22   460.1 1049.26   511.2 1052.01   560.0 1078.56   589.3 1103.63
   599.0 1107.43   618.6 1123.79   667.4 1150.17   726.0 1168.29   765.0 1184.15
   784.5 1189.17   872.4 1222.74   891.9 1232.30   901.7 1233.78   921.2 1241.32
#Mann= 3 , 0 , 0
       0     0.1       0   445.1   0.045       0   460.1     0.1       0
Bank Sta=   445.1,   460.1
Exp/Cntr=0.3,0.1

Type RM Length L Ch R = 1 ,381,336.42,344.327,349.648
XS GIS Cut Line= 3
     1697941.963      387353.314     1697817.239      386915.267
     1697680.415      386481.368
#Sta/Elev= 30
       0 1147.10    38.8 1143.60    77.5 1135.94   116.3 1124.85   145.4 1113.25
   155.0 1113.04   213.2 1094.06   232.6 1089.52   261.6 1076.29   281.0 1070.90
   300.4 1062.82   310.1 1062.36   339.2 1053.27   542.5 1047.53   542.6 1047.52
   557.5 1047.98   571.6 1050.22   600.7 1058.93   629.7 1079.15   639.4 1081.68
   668.4 1104.37   687.8 1112.56   707.1 1126.86   745.9 1144.99   765.2 1150.15
   803.9 1165.07   833.0 1187.05   871.7 1203.80   891.1 1208.78   910.4 1217.40
#Mann= 3 , 0 , 0
       0     0.1       0   542.5   0.045       0   557.5     0.1       0
Bank Sta=   542.5,   557.5
Exp/Cntr=0.3,0.1

Type RM Length L Ch R = 1 ,36.6,42.632,36.636,33.225
XS GIS Cut Line= 5
     1697988.261      387419.793     1698069.923      387114.448
     1698087.220      386689.404     1698065.381      386395.144
     1698020.117      386201.074
#Sta/Elev= 30
       0 1146.73    38.3 1140.26    67.0 1133.53   105.4 1119.83   134.1 1107.36
   143.7 1105.82   182.0 1094.26   210.7 1078.82   229.9 1071.93   249.0 1063.48
   287.3 1054.53   403.1 1050.87   519.1 1051.86   577.1 1050.93     734 1042.48
     749 1042.41   859.5 1043.91   928.3 1048.46   948.0 1051.34   957.9 1055.22
   977.5 1065.48   987.4 1074.68   997.2 1081.63  1007.0 1084.27  1036.5 1099.88
  1074.5 1115.18  1140.9 1132.27  1159.9 1140.84  1188.4 1145.91  1235.8 1150.31
#Mann= 3 , 0 , 0
       0     0.1       0     734   0.045       0     749     0.1       0
Bank Sta=     734,     749
Exp/Cntr=0.3,0.1